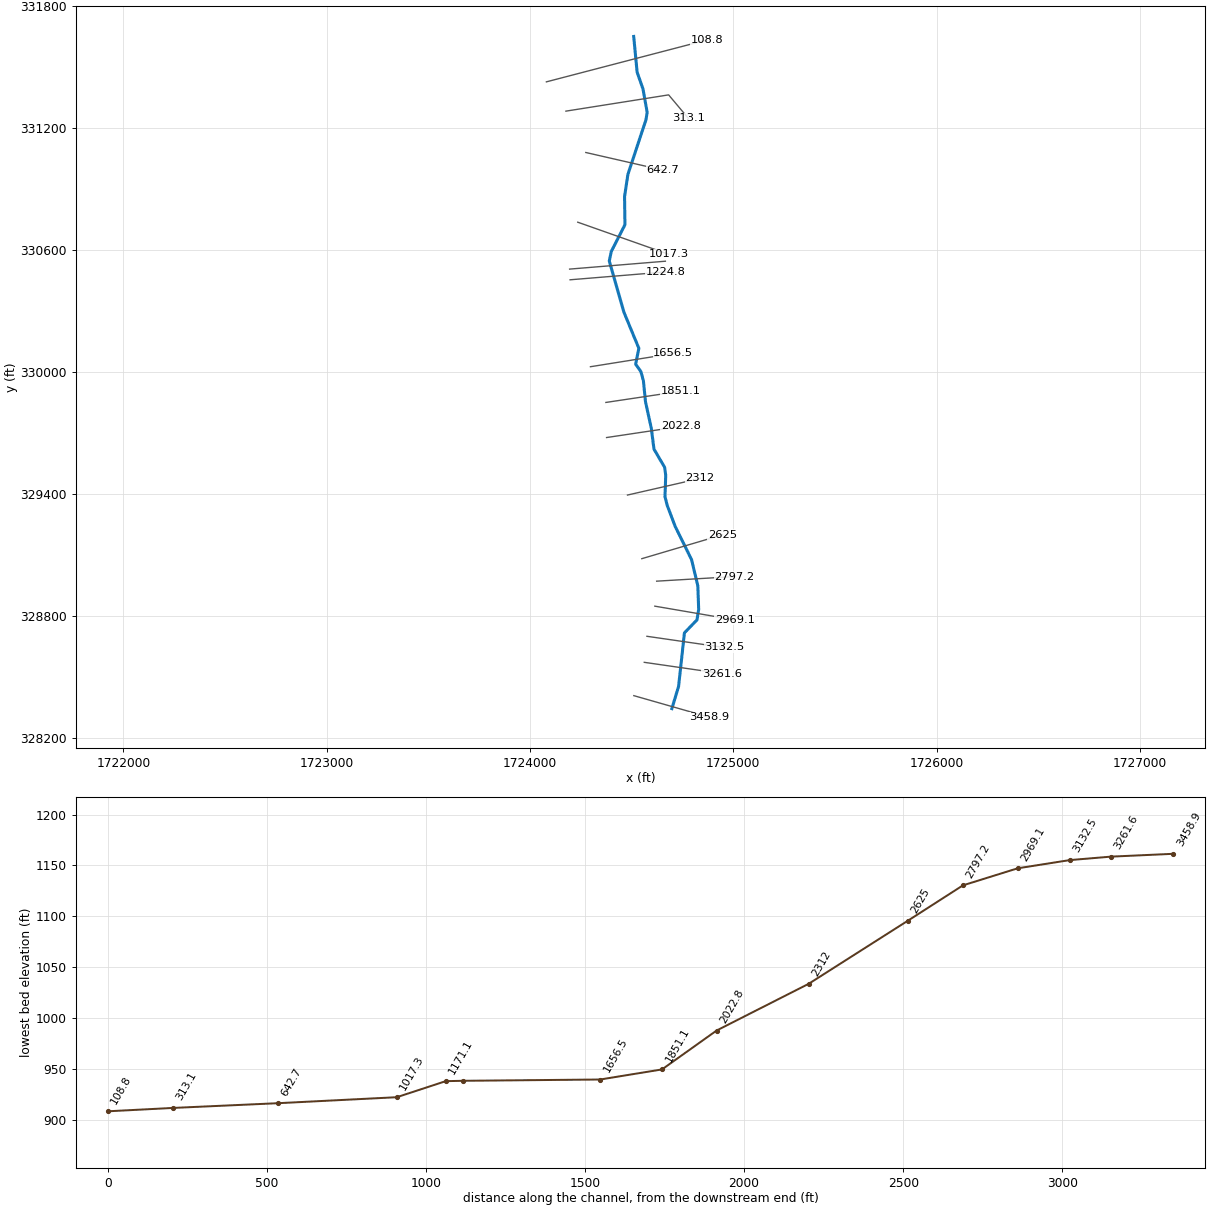
--- LEFTHVFRK.prj (project) ---

Proj Title=LEFTHVFRK
Current Plan=p01
Default Exp/Contr=0,0
English Units
Geom File=g01
Flow File=f01
Plan File=p01
BEGIN DESCRIPTION:
END DESCRIPTION:
DSS Export Rating Curves= 0
DSS Export Rating Curve Sorted= 0
DSS Export Volume Flow Curves= 0
DXF OffsetX= 0
DXF OffsetY= 0
DXF ScaleX= 0
DXF ScaleY= 0

--- LEFTHVFRK.p01 (plan) ---

Plan Title=Floodplain
Program Version=4.00
Geom File=g01
Flow File=f01
K Sum by GR=0
Std Step Tol=0.01
Critical Tol=0.01
Num of Std Step Trials=20
Max Error Tol=0.3
Flow Tol Ratio=0.001
Split Flow NTrial=30
Split Flow Tol=0.02
Split Flow Ratio=0.02
Log Output Level=0
Friction Slope Method=1
Unsteady Friction Slope Method=2
Unsteady Bridges Friction Slope Method=1
Global Log Level=0
CheckData=False
Run HTab=0
Run UNet=0
Run PostProcess=0
UNET Theta=0
UNET Theta Warmup=0
UNET ZTol=0
UNET ZSATol=0
UNET MxIter=0
UNET MaxInSteps=0
UNET DtIC=0
UNET DtMin=0
UNET MaxCRTS=0
UNET WFStab=0
UNET SFStab=0
UNET WFX=0
UNET SFX=0
UNET DSS MLevel=0
UNET DZMax Abort=0
UNET Convert EG Bridges=0
UNET Use Existing IB Tables=0
UNET Froude Limit=0
UNET Froude Power=0
Write IC File=0
Echo Input=False
Echo Output=False
Write Detailed=0

--- LEFTHVFRK.f01 (steady flow) ---

Flow Title=NFF Regression Equation
Program Version=4.00
Number of Profiles=1
Profile Names=P100yr
River Rch & RM=LEFTHVFRK,Main      ,3458.9
918.3981
River Rch & RM=LEFTHVFRK,Main      ,108.8
993.5687
Boundary for River Rch & Prof#=LEFTHVFRK,Main      ,1
Up Type=0
Dn Type=3
Dn Slope=0.015366

--- LEFTHVFRK.g01 (geometry) ---

Geom Title=USGS 10m DEM
Program Version=4.10

River Reach=LEFTHVFRK       ,Main
Reach XY= 30
     1724697.698      328345.027     1724730.642      328454.156
     1724759.469      328717.711      1724821.24      328781.541
     1724829.475      328833.017     1724825.357      328948.322
     1724794.472      329078.041      1724714.17      329240.704
     1724675.049      329343.656     1724663.868      329386.981
      1724667.48       329492.71     1724661.858      329532.066
     1724609.652      329621.219     1724596.805      329722.517
     1724567.979      329854.294     1724557.684      329957.246
      1724545.33      330002.544     1724519.574      330039.028
     1724535.334      330116.967     1724461.895      330294.485
     1724389.907      330546.174     1724399.837       330593.34
      1724466.89      330724.398     1724465.028      330863.218
       1724481.5      330972.347     1724570.038       331240.02
     1724576.215      331277.083     1724555.625      331392.388
     1724526.799      331474.749     1724509.959      331650.546

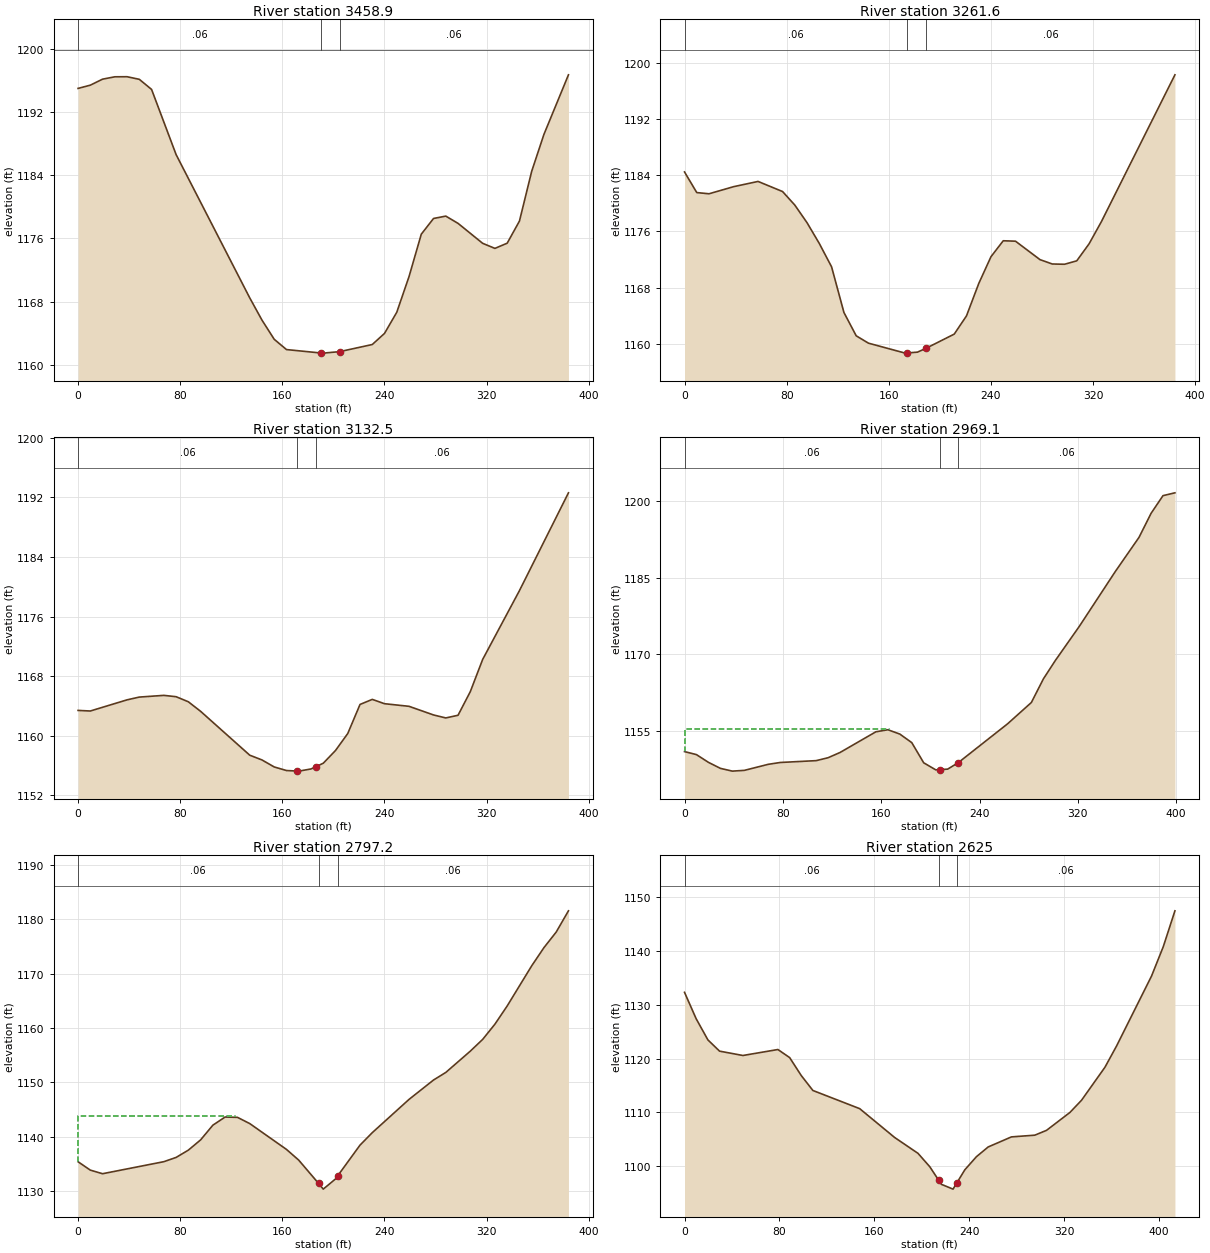
Type RM Length L Ch R = 1 ,3458.9  ,194.2,197.3,200.3
XS GIS Cut Line= 2
     1724510.571      328408.891      1724879.97       328303.35
#Sta/Elev= 30
       0    1195     9.6 1195.41    19.2 1196.17    28.8 1196.47    38.4 1196.48
      48 1196.15    57.6 1194.87    76.8 1186.62   134.5 1168.46   144.1 1165.64
   153.7 1163.21   163.3 1161.91     190 1161.48   192.1 1161.46     205 1161.65
   230.5 1162.55   240.1 1163.96   249.7 1166.64   259.3 1171.16   268.9 1176.53
   278.5 1178.52   288.1 1178.82   297.7  1177.9     317 1175.37   326.6 1174.73
   336.2 1175.39   345.8 1178.19   355.4  1184.5     365 1189.18   384.2 1196.72
#Mann= 3 , 0 , 0
       0     .06       0     190    .045       0     205     .06       0
Bank Sta=190,205
XS Rating Curve= 0 ,0
Exp/Cntr=0.3,0.1

Type RM Length L Ch R = 1 ,3261.6  ,129,129,129
XS GIS Cut Line= 2
     1724561.903      328572.763     1724942.127      328517.774
#Sta/Elev= 30
       0 1184.48     9.6 1181.54    19.2 1181.37    38.4 1182.38    57.6 1183.13
    76.8 1181.69    86.4 1179.76      96 1177.24   105.6 1174.28   115.2 1170.96
   124.9 1164.44   134.5 1161.12   144.1 1160.07   172.9 1158.65   174.2 1158.67
   182.5 1158.79   189.2 1159.34   211.3 1161.36   220.9 1163.96   230.5 1168.57
   240.1  1172.4   249.7 1174.67   259.3 1174.61   278.5 1171.98   288.1 1171.36
   297.7 1171.32   307.3 1171.81     317 1174.25   326.6  1177.4   384.2 1198.33
#Mann= 3 , 0 , 0
       0     .06       0   174.2    .045       0   189.2     .06       0
Bank Sta=174.2,189.2
XS Rating Curve= 0 ,0
Exp/Cntr=0.3,0.1

Type RM Length L Ch R = 1 ,3132.5  ,164,163.4,162.9
XS GIS Cut Line= 2
     1724574.998      328700.802     1724955.222      328645.812
#Sta/Elev= 30
       0  1163.4     9.6 1163.32    38.4 1164.82      48 1165.19    67.2 1165.42
    76.8 1165.24    86.4 1164.56      96 1163.28   134.5 1157.39   144.1 1156.75
   153.7 1155.81   163.3 1155.33   171.4 1155.26   172.9 1155.25   182.5 1155.54
   186.4 1155.85   192.1 1156.31   201.7 1158.02   211.3  1160.3   220.9  1164.2
   230.5 1164.88   240.1  1164.3   259.3 1163.95   278.5 1162.79   288.1 1162.39
   297.7 1162.75   307.3 1165.92     317 1170.25   345.8 1179.48   384.2 1192.61
#Mann= 3 , 0 , 0
       0     .06       0   171.4    .045       0   186.4     .06       0
Bank Sta=171.4,186.4
XS Rating Curve= 0 ,0
Exp/Cntr=0.3,0.1

Type RM Length L Ch R = 1 ,2969.1  ,166.7,171.9,177
XS GIS Cut Line= 2
      1724613.96      328848.938     1725007.275      328781.573
#Sta/Elev= 30
       0 1150.99     9.7  1150.4    19.5 1148.88    29.2 1147.71    38.9 1147.17
    48.7 1147.32    68.1  1148.5    77.9 1148.86   107.1 1149.22   116.8 1149.79
   126.5 1150.81   155.7 1154.86   165.5 1155.26   175.2 1154.41   184.9 1152.74
   194.6  1148.8   204.4 1147.42   207.8 1147.47   214.1 1147.56   222.8 1148.84
   262.8 1156.41   282.2 1160.59     292 1165.21   301.7  1168.8   321.2 1175.47
   350.4 1186.16   369.8 1192.88   379.6 1197.57   389.3 1201.03     399 1201.58
#Mann= 3 , 0 , 0
       0     .06       0   207.8    .045       0   222.8     .06       0
#XS Ineff= 2 , 0
          166.01 1155.39
Permanent Ineff=
       F       F
Bank Sta=207.8,222.8
XS Rating Curve= 0 ,0
Exp/Cntr=0.3,0.1

Type RM Length L Ch R = 1 ,2797.2  ,167.2,172.4,177.5
XS GIS Cut Line= 2
     1724622.824      328971.875     1725006.334      328994.562
#Sta/Elev= 30
       0 1135.43     9.6 1133.89    19.2 1133.23    67.2 1135.44    76.8 1136.22
    86.4 1137.56      96 1139.44   105.6 1142.14   115.2 1143.64   124.9 1143.58
   134.5 1142.44   163.3 1137.69   172.9 1135.72   188.4 1131.46   192.1  1130.4
   201.7 1132.27   203.4 1132.84   220.9 1138.48   230.5 1140.77   259.3 1146.88
   278.5 1150.44   288.1 1151.83   307.3 1155.74     317  1157.9   326.6  1160.7
   336.2 1164.04   355.4 1171.41     365 1174.75   374.6 1177.61   384.2 1181.51
#Mann= 3 , 0 , 0
       0     .06       0   188.4    .045       0   203.4     .06       0
#XS Ineff= 2 , 0
          123.01 1143.82
Permanent Ineff=
       F       F
Bank Sta=188.4,203.4
XS Rating Curve= 0 ,0
Exp/Cntr=0.3,0.1

Type RM Length L Ch R = 1 ,2625    ,313.8,312.5,311.2
XS GIS Cut Line= 2
     1724549.829      329082.436      1724946.15      329199.724
#Sta/Elev= 30
       0 1132.31     9.8 1127.41    19.7 1123.48    29.5 1121.39    49.2 1120.58
    78.7 1121.69    88.6 1120.19    98.4 1116.85   108.2 1114.08   147.6 1110.71
   177.1 1105.35   196.8  1102.4   206.7 1099.92   214.3 1097.38   216.5 1096.65
   226.3 1095.76   229.3 1096.84   236.2 1099.34     246 1101.78   255.9 1103.59
   275.5 1105.46   295.2 1105.78   305.1 1106.68   324.8    1110   334.6 1112.27
   354.3 1118.39   364.1 1122.34   393.6 1135.34   403.5  1140.8   413.3 1147.45
#Mann= 3 , 0 , 0
       0     .06       0   214.3    .045       0   229.3     .06       0
Bank Sta=214.3,229.3
XS Rating Curve= 0 ,0
Exp/Cntr=0.3,0.1

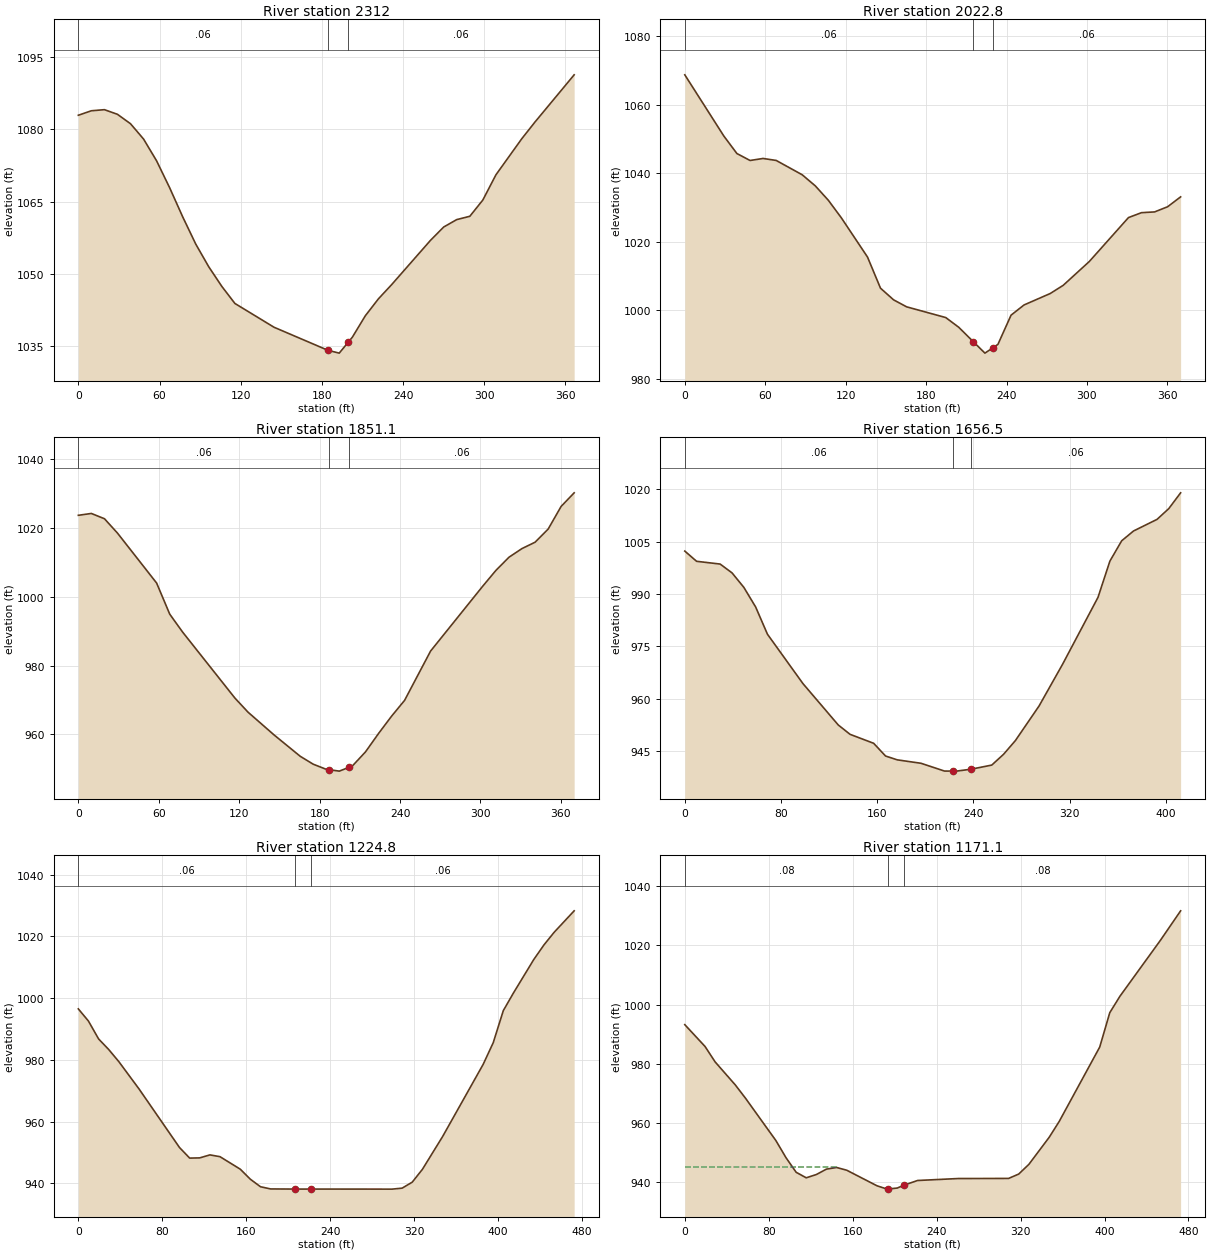
Type RM Length L Ch R = 1 ,2312    ,291.1,289.3,287.5
XS GIS Cut Line= 2
     1724479.389      329395.377     1724836.599      329476.919
#Sta/Elev= 30
       0 1082.93     9.6 1083.86    19.3 1084.09    28.9 1083.13    38.6 1081.16
    48.2 1077.99    57.8 1073.48    67.5 1067.86    77.1 1061.84    86.8 1056.15
    96.4 1051.44   106.1 1047.35   115.7 1043.83   144.6 1038.89   184.6 1034.08
   192.8 1033.51   199.6 1035.83   202.5 1036.82   212.1 1041.28   221.8  1044.8
   231.4  1047.7   260.3 1056.96     270 1059.71   279.6 1061.25   289.3 1061.94
   298.9 1065.31   308.6 1070.56   327.8 1078.09   337.5 1081.54   366.4 1091.33
#Mann= 3 , 0 , 0
       0     .06       0   184.6    .045       0   199.6     .06       0
Bank Sta=184.6,199.6
XS Rating Curve= 0 ,0
Exp/Cntr=0.3,0.1

Type RM Length L Ch R = 1 ,2022.8  ,171.6,171.6,171.6
XS GIS Cut Line= 2
     1724376.609      329678.192      1724742.47      329732.933
#Sta/Elev= 30
       0 1068.71    29.2 1050.82    38.9 1045.75    48.7 1043.73    58.4 1044.32
    68.2 1043.74    87.6 1039.56    97.4 1036.31   107.1 1032.12   116.8    1027
   136.3 1015.58     146 1006.49   155.8 1003.08   165.5 1001.05   194.7  997.92
   204.4  995.08   215.1  990.94   223.9  987.55   230.1  989.18   233.6   990.1
   243.4  998.62   253.1  1001.6   272.6 1004.93   282.3 1007.32   301.8 1014.28
     331 1027.08   340.7 1028.51   350.5 1028.73   360.2 1030.24   369.9 1033.12
#Mann= 3 , 0 , 0
       0     .06       0   215.1    .045       0   230.1     .06       0
Bank Sta=215.1,230.1
XS Rating Curve= 0 ,0
Exp/Cntr=0.3,0.1

Type RM Length L Ch R = 1 ,1851.1  ,194.1,194.4,194.6
XS GIS Cut Line= 2
     1724373.225      329850.805     1724739.086      329905.546
#Sta/Elev= 30
       0  1023.7     9.7 1024.24    19.5  1022.7    29.2 1018.53    58.4    1004
    68.2  994.94    77.9  989.68   116.8  970.54   126.6  966.43     146  959.82
   165.5  953.61   175.2   951.3     185   949.8   186.7  949.71   194.7  949.28
   201.7  950.35   204.4  950.76   214.2  954.86   223.9  960.19   233.6  965.22
   243.4  969.87   262.8  984.21   301.8 1003.13   311.5 1007.66   321.3 1011.51
     331 1014.03   340.7 1015.86   350.5 1019.69   360.2  1026.3   369.9 1030.24
#Mann= 3 , 0 , 0
       0     .06       0   186.7    .045       0   201.7     .06       0
Bank Sta=186.7,201.7
XS Rating Curve= 0 ,0
Exp/Cntr=0.3,0.1

Type RM Length L Ch R = 1 ,1656.5  ,433.4,431.6,429.9
XS GIS Cut Line= 2
     1724297.241      330026.432     1724704.327      330091.496
#Sta/Elev= 30
       0 1002.28     9.8  999.36    29.4  998.57    39.3  996.04    49.1   991.9
    58.9   986.3    68.7  978.52    98.2   964.4   127.6  952.55   137.4  949.88
     157  947.32   166.9  943.68   176.7  942.58   196.3  941.61   215.9  939.38
     223  939.37   225.8  939.36     238  939.91   255.2  941.09     265  944.17
   274.8  948.08   294.5  957.98   314.1  969.94   343.5  989.04   353.4  999.41
   363.2 1005.22     373 1008.02   392.6 1011.35   402.4 1014.44   412.2 1018.94
#Mann= 3 , 0 , 0
       0     .06       0     223    .045       0     238     .06       0
Bank Sta=223,238
XS Rating Curve= 0 ,0
Exp/Cntr=0.3,0.1

Type RM Length L Ch R = 1 ,1224.8  ,53.6,53.6,53.6
XS GIS Cut Line= 2
     1724197.126      330453.935     1724668.074      330492.732
#Sta/Elev= 30
       0  996.52     9.6   992.6    19.3  986.79    28.9  983.37    38.6  979.42
    57.9  970.54    96.4  951.58   106.1  948.14   115.7  948.21   125.4  949.18
     135   948.6   154.3  944.55   163.9   941.3   173.6  938.85   183.2  938.14
   206.8   938.1   221.8   938.1     299  938.08   308.6   938.4   318.2  940.34
   327.9   944.5   347.2  955.16   385.8  978.54   395.4  985.58     405  995.97
   414.7 1001.71     434 1012.52   443.6 1017.21   453.3 1021.31   472.5 1028.32
#Mann= 3 , 0 , 0
       0     .06       0   206.8    .045       0   221.8     .06       0
Bank Sta=206.8,221.8
XS Rating Curve= 0 ,0
Exp/Cntr=0.3,0.1

Type RM Length L Ch R = 1 ,1171.1  ,163.7,153.9,144.2
XS GIS Cut Line= 2
      1724194.84       330506.51     1724665.788      330545.308
#Sta/Elev= 30
       0  993.22    19.3  985.86    28.9  980.66    48.2  972.86    57.9  968.38
    86.8  954.13    96.4  948.37   106.1  943.43   115.7  941.56   125.4  942.67
     135  944.49   144.7  945.04   154.3  944.12   183.2  938.86   192.9  937.74
   194.1  937.79   202.5  938.11   209.1  939.11   221.8  940.65   260.4  941.31
   308.6  941.35   318.2  942.82   327.9   946.1   347.2   955.2   356.8  960.57
   395.4  985.66     405  997.27   414.7 1002.82   453.3  1021.7   472.5 1031.62
#Mann= 3 , 0 , 0
       0     .08       0   194.1    .045       0   209.1     .08       0
#XS Ineff= 2 , 0
          144.51  945.13
Permanent Ineff=
       F       F
Bank Sta=194.1,209.1
XS Rating Curve= 0 ,0
Exp/Cntr=0.3,0.1

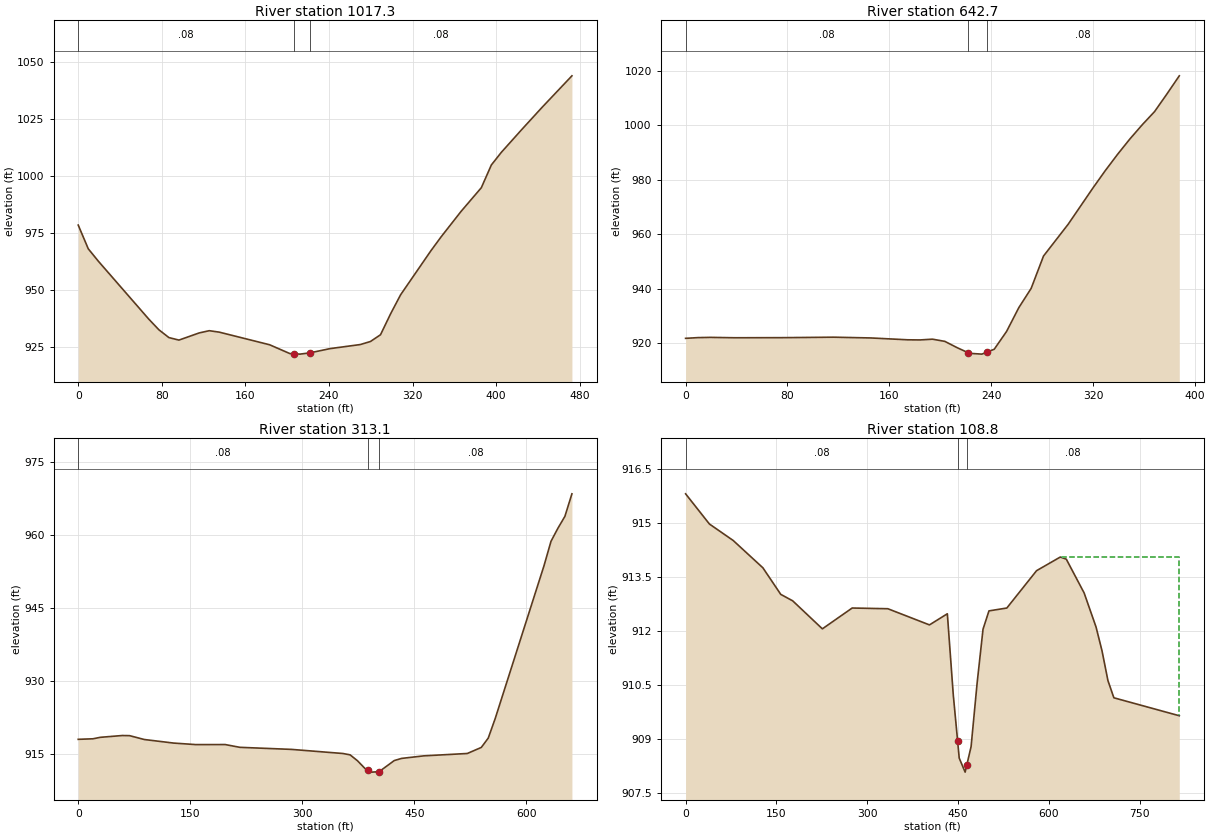
Type RM Length L Ch R = 1 ,1017.3  ,371.8,374.5,377.3
XS GIS Cut Line= 2
     1724234.944      330737.128     1724680.547      330579.854
#Sta/Elev= 30
       0   978.5     9.6  968.12    19.3  962.65    67.5   937.3    77.2  932.61
    86.8  929.19    96.4  928.09   115.7  931.22   125.4  932.21     135  931.57
   183.2  926.04   202.5  922.19   206.6  922.08   212.2  921.94   221.6  922.48
   241.1  924.36     270  926.14   279.7  927.48   289.3  930.43     299  939.64
   308.6  947.99   337.5  967.22   347.2  973.28   366.5  984.55   385.8  994.88
   395.4 1004.85     405 1010.41   424.3 1020.28   443.6 1029.94   472.5 1043.92
#Mann= 3 , 0 , 0
       0     .08       0   206.6    .045       0   221.6     .08       0
Bank Sta=206.6,221.6
XS Rating Curve= 0 ,0
Exp/Cntr=0.3,0.1

Type RM Length L Ch R = 1 ,642.7   ,321,329.6,338.2
XS GIS Cut Line= 2
     1724274.487      331079.904     1724652.336      330993.439
#Sta/Elev= 30
       0  921.83     9.7  922.09    19.4  922.18    38.8  922.04    77.5  922.08
   116.3  922.25   145.4  921.97   174.4  921.29   184.1  921.24   193.8  921.52
   203.5  920.72   213.2   918.4   221.6   916.6   222.9  916.32   232.6  916.03
   236.6  916.77   242.3  917.82     252  924.36   261.6  933.09   271.3  940.17
     281  952.05   300.4  963.75   319.8  977.04   329.5  983.42   339.2  989.43
   348.8  995.03   358.5 1000.25   368.2  1005.1   377.9 1011.57   387.6 1018.23
#Mann= 3 , 0 , 0
       0     .08       0   221.6    .045       0   236.6     .08       0
Bank Sta=221.6,236.6
XS Rating Curve= 0 ,0
Exp/Cntr=0.3,0.1

Type RM Length L Ch R = 1 ,313.1   ,201.9,204.3,206.7
XS GIS Cut Line= 3
      1724176.58      331283.301     1724681.764      331363.307
     1724777.772      331249.012
#Sta/Elev= 30
       0   918.1    19.7  918.21    29.5  918.51      59  918.88    68.8  918.85
    88.5  918.06   127.9  917.33   157.4  917.02   196.7  917.03   216.4  916.46
   285.2  916.04   354.1   915.2   363.9  914.92   373.8  913.71   383.6  912.16
   387.8  911.83   393.4  911.38   402.8  911.48     423  913.75   432.8  914.19
   462.3  914.71   520.8   915.2   539.5  916.44   548.8  918.35   558.1  922.35
   623.4  953.65   632.8  958.67   642.1  961.36   651.4  963.78   660.8   968.4
#Mann= 3 , 0 , 0
       0     .08       0   387.8    .045       0   402.8     .08       0
Bank Sta=387.8,402.8
XS Rating Curve= 0 ,0
Exp/Cntr=0.3,0.1

Type RM Length L Ch R = 1 ,108.8   ,111.9,108.8,105.6
XS GIS Cut Line= 2
     1724080.573      331427.312     1724869.208      331633.043
#Sta/Elev= 30
       0  915.82    39.3  914.98    78.6  914.52   127.6  913.76   157.1  913.02
   176.8  912.84   225.8  912.06     275  912.64   333.9  912.62   402.6  912.17
   432.1  912.48   441.9  910.22   449.1  908.93   451.7  908.46   461.5  908.07
   464.1  908.26   471.3  908.78   481.2  910.54     491  912.05   500.8  912.56
   530.3  912.64   579.4  913.68   618.6  914.06   628.5     914   657.9  913.06
   677.6  912.11   687.4  911.45   697.2  910.62     707  910.14     815  909.64
#Mann= 3 , 0 , 0
       0     .08       0   449.1    .045       0   464.1     .08       0
#XS Ineff= 2 , 0
                          621.97          914.07
Permanent Ineff=
       F       F
Bank Sta=449.1,464.1
XS Rating Curve= 0 ,0
Exp/Cntr=0.3,0.1

Chan Stop Cuts=-1
Use User Specified Reach Order=0
Composite Channel Slope=5